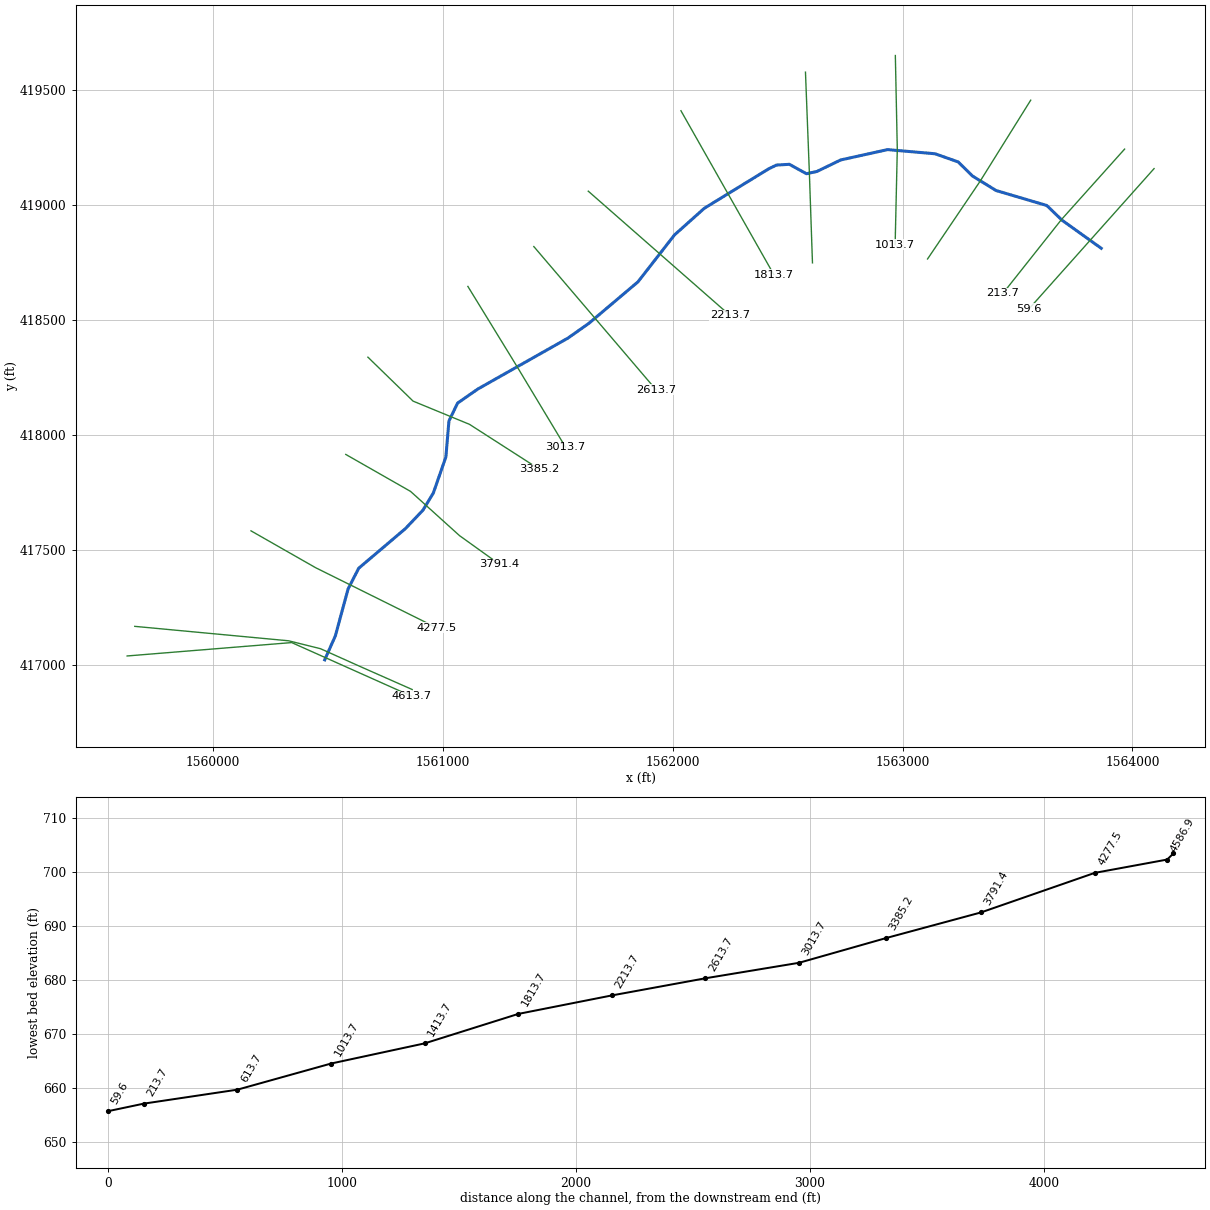
--- RFLYNNCR.prj (project) ---

Proj Title=RFLYNNCR
Current Plan=p01
Default Exp/Contr=0,0
English Units
Geom File=g01
Flow File=f01
Plan File=p01
BEGIN DESCRIPTION:
END DESCRIPTION:
DSS Export Rating Curves= 0
DSS Export Rating Curve Sorted= 0
DSS Export Volume Flow Curves= 0
DXF OffsetX= 0
DXF OffsetY= 0
DXF ScaleX= 0
DXF ScaleY= 0

--- RFLYNNCR.p01 (plan) ---

Plan Title=Floodplain
Program Version=4.00
Geom File=g01
Flow File=f01
K Sum by GR=0
Std Step Tol=0.01
Critical Tol=0.01
Num of Std Step Trials=20
Max Error Tol=0.3
Flow Tol Ratio=0.001
Split Flow NTrial=30
Split Flow Tol=0.02
Split Flow Ratio=0.02
Log Output Level=0
Friction Slope Method=1
Unsteady Friction Slope Method=2
Unsteady Bridges Friction Slope Method=1
Global Log Level=0
CheckData=False
Run HTab=0
Run UNet=0
Run PostProcess=0
UNET Theta=0
UNET Theta Warmup=0
UNET ZTol=0
UNET ZSATol=0
UNET MxIter=0
UNET MaxInSteps=0
UNET DtIC=0
UNET DtMin=0
UNET MaxCRTS=0
UNET WFStab=0
UNET SFStab=0
UNET WFX=0
UNET SFX=0
UNET DSS MLevel=0
UNET DZMax Abort=0
UNET Convert EG Bridges=0
UNET Use Existing IB Tables=0
UNET Froude Limit=0
UNET Froude Power=0
Write IC File=0
Echo Input=False
Echo Output=False
Write Detailed=0

--- RFLYNNCR.f01 (steady flow) ---

Flow Title=NFF Regression Equation
Program Version=4.00
Number of Profiles= 1
Profile Names=P100yr
River Rch & RM=RFLYNNCR,Main            ,4613.7
     311
River Rch & RM=RFLYNNCR,Main            ,4277.5
     469
River Rch & RM=RFLYNNCR,Main            ,3385.2
     489
Boundary for River Rch & Prof#=RFLYNNCR,Main            , 1
Up Type= 0
Dn Type= 3
Dn Slope=0.009246
DSS Import GetInterval= 0
DSS Import GetPeak= 0
DSS Import FillOption= 0

--- RFLYNNCR.g01 (geometry) ---

Geom Title=USGS 10m DEM
Program Version=4.00

River Reach=RFLYNNCR        ,Main
Reach XY= 30
     1560485.754      417022.231     1560532.153      417126.956
     1560587.343      417330.389     1560633.618      417420.769
      1560837.14      417593.545     1560912.855      417673.157
     1560958.264      417747.984     1561013.012      417905.258
     1561026.188      418061.175     1561063.768      418139.297
     1561152.125      418200.707      1561543.75      418422.018
     1561635.043      418486.376       1561848.6      418666.821
     1562007.747      418871.235     1562137.478      418987.085
     1562416.895      419158.349     1562451.044      419174.984
     1562507.411      419178.338      1562581.81      419137.338
     1562627.331      419147.206     1562730.696      419197.282
     1562934.657      419242.286     1563141.323      419224.245
     1563242.226      419188.583     1563304.264      419127.321
     1563406.968       419064.22     1563627.482      418999.146
     1563693.009      418935.756     1563864.431      418812.882

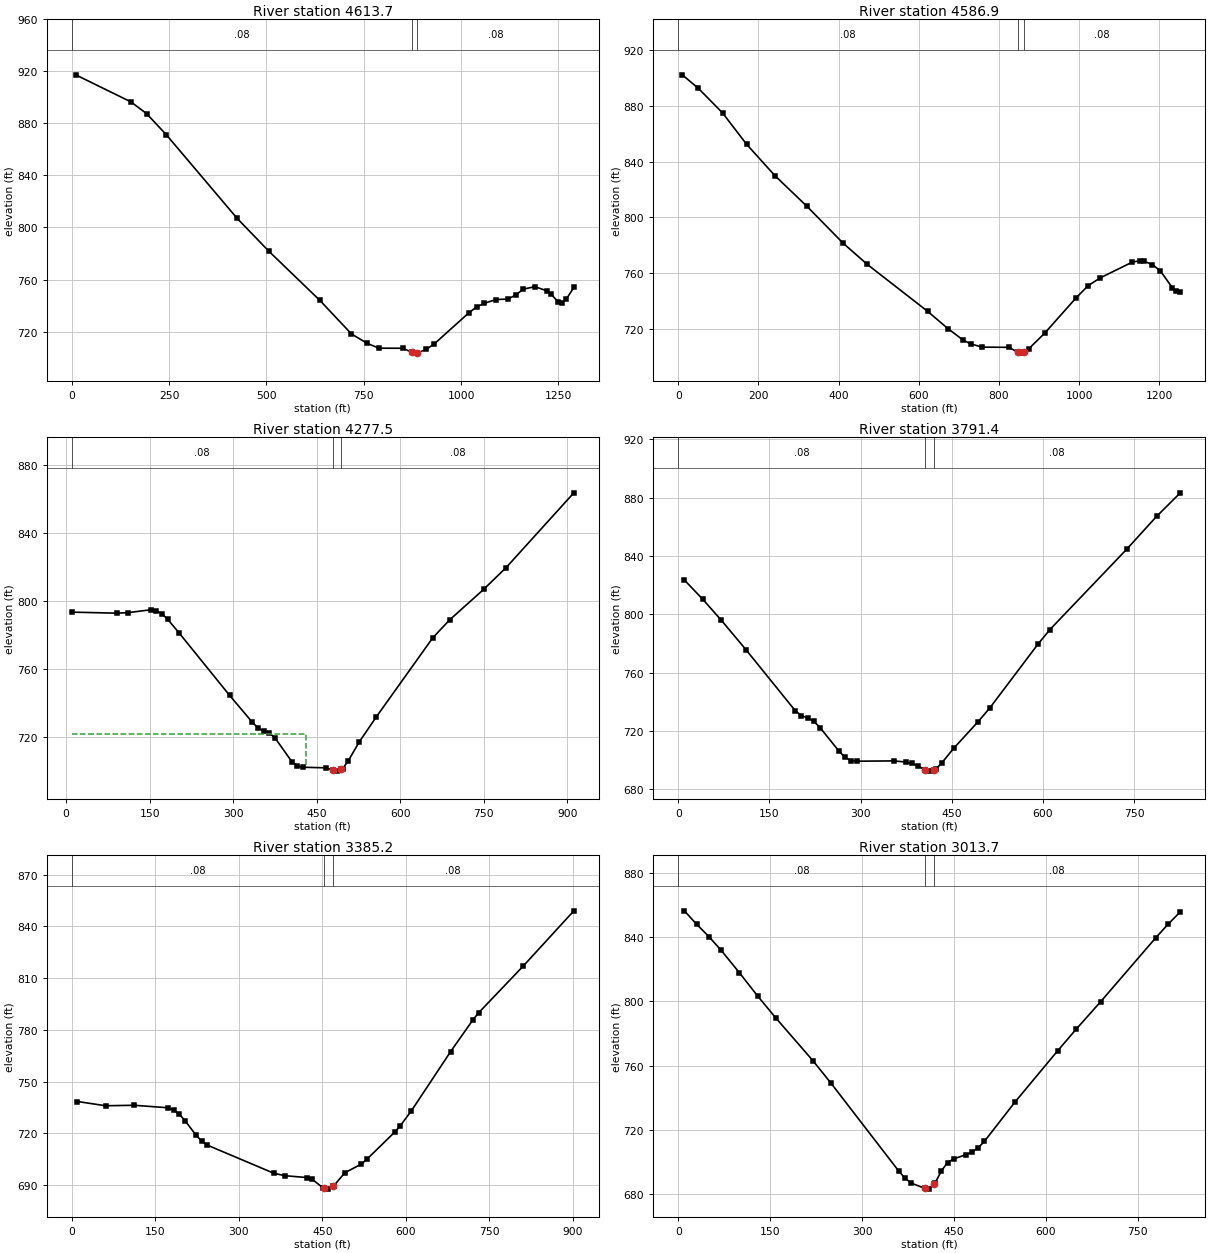
Type RM Length L Ch R = 1 ,4613.7  ,26.8,26.8,26.7
XS GIS Cut Line= 4
     1559626.087      417039.186     1560342.083       417097.41
     1560489.835       417031.36     1560863.681      416864.239
#Sta/Elev= 30
    10.1  917.31   151.8  896.55   192.2   887.5   242.8  871.29   424.9  806.98
   505.9  781.88   637.4  743.94   718.4  718.23   758.8  710.94   789.2  707.26
   849.9  707.21   872.7  704.32   880.2  703.46   887.7  703.65   910.2  706.29
   930.1  710.24    1020  734.44    1040  738.96    1060  741.81  1089.9  744.64
  1119.9     745  1139.9  747.98  1159.9  752.66  1189.8  754.51  1219.8  751.39
  1229.8  749.23  1249.8  742.68  1259.7  742.22  1269.7  744.69  1289.7  753.92
#Mann= 3 , 0 , 0
       0     .08       0   872.7    .045       0   887.7     .08       0
Bank Sta=872.7,887.7
XS Rating Curve= 0 ,0
Exp/Cntr=0.3,0.1

Type RM Length L Ch R = 1 ,4586.9  ,310.3,309.5,308.6
XS GIS Cut Line= 5
     1559659.324      417168.004     1560328.734      417105.183
     1560467.213       417070.85     1560637.736      416994.308
     1560866.399      416893.169
#Sta/Elev= 30
      10   902.5    50.2  892.79   110.4  875.15   170.6  852.49   240.8  830.07
   321.1  807.87   411.4  781.34   471.6   766.1   622.2  732.31   672.4  719.98
   710.4  711.71   729.4  708.95     758  706.63   824.9  706.49   846.9  702.87
   854.4  702.32   861.9  702.99     874  705.39   913.4  716.56   992.1  742.07
  1021.9  750.77  1051.9  756.39    1132  767.74    1152   768.8    1162  768.39
    1182  766.05    1202  761.59    1232  749.42    1242  746.69    1252  746.52
#Mann= 3 , 0 , 0
       0     .08       0   846.9    .045       0   861.9     .08       0
Bank Sta=846.9,861.9
XS Rating Curve= 0 ,0
Exp/Cntr=0.3,0.1

Type RM Length L Ch R = 1 ,4277.5  ,492.3,486,479.7
XS GIS Cut Line= 3
     1560165.021      417583.554     1560446.451      417423.051
     1560973.005      417161.888
#Sta/Elev= 30
    10.1  793.45    91.1  792.83   111.4  793.15   151.9  794.84     162  794.25
   172.1  792.42   182.2  789.26   202.5  781.34   293.6  744.41   334.1  728.71
   344.3  725.32   354.4  723.36   364.5  722.36   374.7  719.58   405.1   705.5
   415.2  702.77   425.3  702.14   465.9  701.79   478.6  700.54   486.1  699.85
   493.6  700.89   496.3  701.27   506.4  705.81   526.7  717.23   557.1  731.84
   658.4  778.35   688.8  788.93   749.6  806.79   790.1  819.68   911.7  863.68
#Mann= 3 , 0 , 0
    10.1     .08       0   478.6    .045       0   493.6     .08       0
#XS Ineff= 2 , 0
          431.49  721.72
Permanent Ineff=
       F       F
Bank Sta=478.6,493.6
XS Rating Curve= 0 ,0
Exp/Cntr=0.3,0.1

Type RM Length L Ch R = 1 ,3791.4  ,398.4,406.2,414
XS GIS Cut Line= 4
     1560577.373      417916.046     1560859.253      417755.189
      1561072.23      417562.775     1561246.647       417437.79
#Sta/Elev= 30
    10.1  823.54    40.6  810.25      71  795.91   111.6   775.7   192.7  733.87
   202.8  730.59     213  728.93   223.1  726.67   233.3  722.36   263.7  706.63
   273.8  702.12     284   699.8   294.1  699.32   354.2  699.54     374  698.78
   383.9  697.87   393.8  696.18   406.1  693.43   413.6  692.52   421.1  693.46
   423.5  693.76   433.4  698.03   453.2  708.15   492.8  726.13   512.6  735.79
   591.8  779.54   611.6   789.6   738.4  844.88   787.1   867.2   826.1  883.33
#Mann= 3 , 0 , 0
       0     .08       0   406.1    .045       0   421.1     .08       0
Bank Sta=406.1,421.1
XS Rating Curve= 0 ,0
Exp/Cntr=0.3,0.1

Type RM Length L Ch R = 1 ,3385.2  ,385.7,371.5,357.1
XS GIS Cut Line= 4
      1560673.74      418339.213     1560870.262      418147.977
     1561115.638      418046.942     1561420.254      417851.312
#Sta/Elev= 30
    10.2  738.54    60.9  736.07   111.7  736.36   172.7  734.91   182.8  733.54
     193  731.22   203.1  727.53   223.4  718.93   233.6  715.55   243.7  713.22
   362.7  696.98   382.3  695.55   421.6  694.48   431.5  693.56   451.1  688.46
   453.4   688.3   460.9  687.76   468.4  689.31   470.8   689.8   490.4  697.26
   519.9  702.25   529.7  705.01   579.8  720.77   589.9  724.46     610  733.21
   680.4   767.5   720.6  785.97   730.6  789.95   811.1  817.16   901.6  849.04
#Mann= 3 , 0 , 0
       0     .08       0   453.4    .045       0   468.4     .08       0
Bank Sta=453.4,468.4
XS Rating Curve= 0 ,0
Exp/Cntr=0.3,0.1

Type RM Length L Ch R = 1 ,3013.7  ,396.5,400,403.7
XS GIS Cut Line= 3
     1561108.698      418646.982     1561322.681      418298.073
     1561533.959      417946.899
#Sta/Elev= 30
      10  856.25    29.9  847.93    49.9  840.28    69.9  831.76    99.8  817.75
   129.8  803.16   159.7   789.4   219.6  763.12   249.6  748.89   359.4  694.58
   369.4  690.22   379.4  687.05   401.8  683.72   409.3  683.18   416.8  686.22
   419.3  687.23   429.3  694.47   439.3   699.7   449.3  701.98   469.3  704.58
   479.3  706.25   489.3  708.88   499.3   712.8   549.2  737.24   619.2  769.31
   649.2  782.64   689.2  799.75   779.1  839.53   799.1  847.91   819.1  855.63
#Mann= 3 , 0 , 0
       0     .08       0   401.8    .045       0   416.8     .08       0
Bank Sta=401.8,416.8
XS Rating Curve= 0 ,0
Exp/Cntr=0.3,0.1

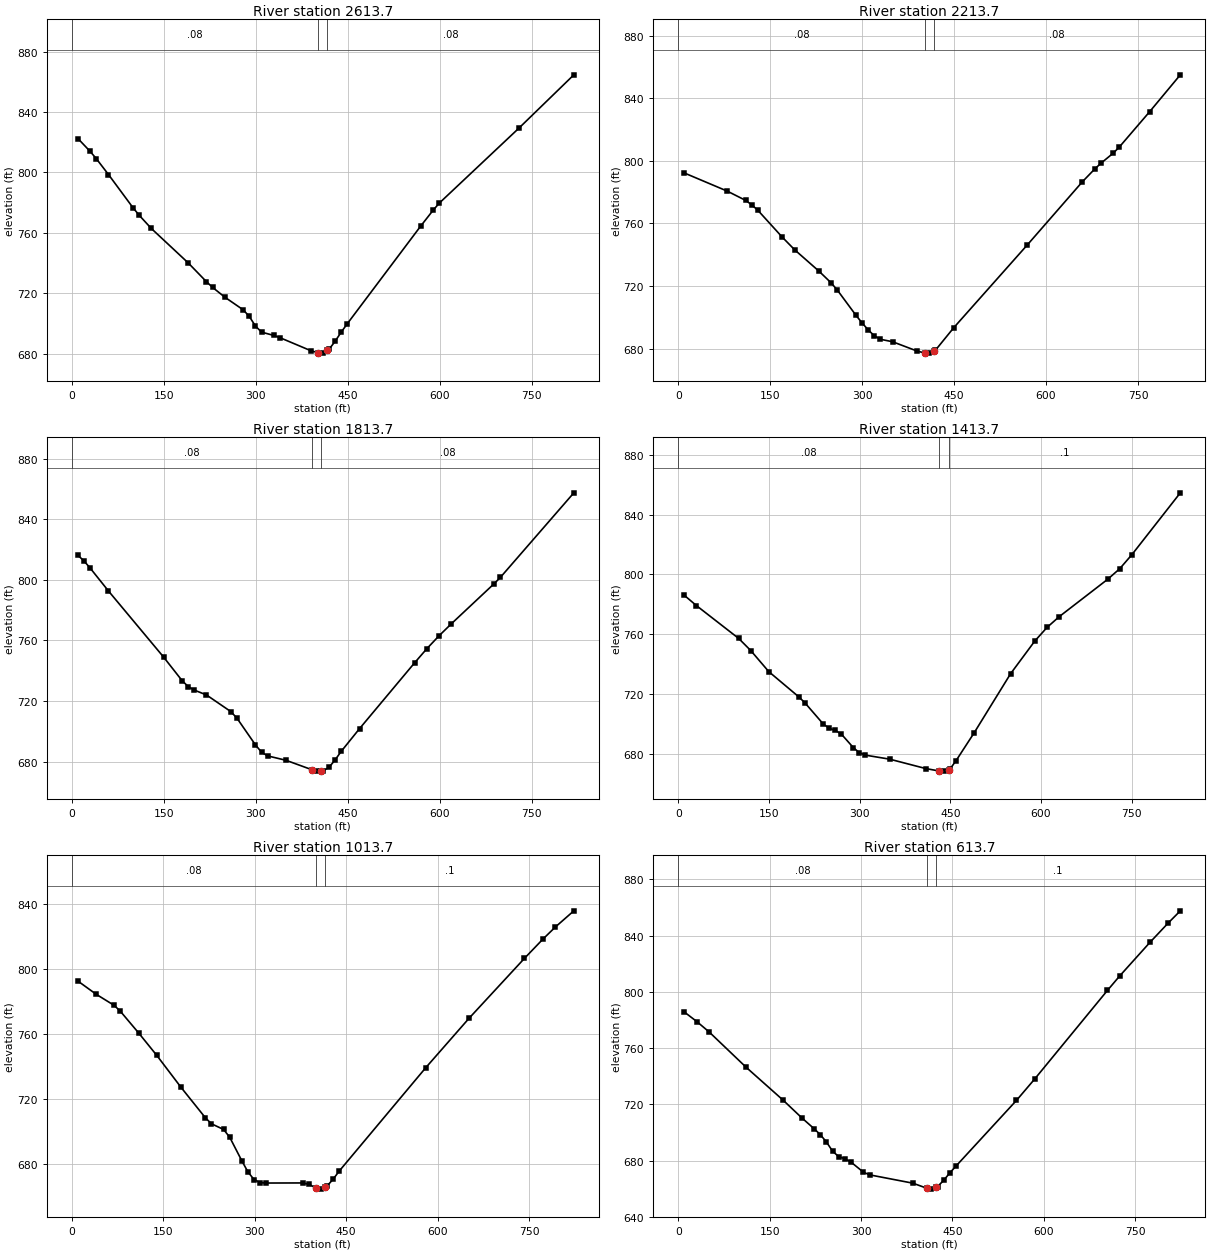
Type RM Length L Ch R = 1 ,2613.7  ,396.7,400,403.3
XS GIS Cut Line= 3
     1561395.648      418820.425     1561661.486      418508.944
     1561927.324      418197.463
#Sta/Elev= 30
      10  822.48      30  813.92      40  809.13    59.9  798.61    99.9  776.62
   109.9  771.67   129.8  762.87   189.8  740.13   219.7  727.62   229.7  723.86
   249.7  717.36   279.7  708.98   289.6   704.6   299.6  698.24   309.6  694.22
   329.6  692.02   339.6  690.54   389.5     682     402  680.52   409.5  680.31
     417  682.14   419.5  682.76   429.5   688.1   439.5  694.23   449.5  699.82
   569.3  764.53   589.3  774.89   599.3  779.61   729.1  829.23     819  864.67
#Mann= 3 , 0 , 0
       0     .08       0     402    .045       0     417     .08       0
Bank Sta=402,417
XS Rating Curve= 0 ,0
Exp/Cntr=0.3,0.1

Type RM Length L Ch R = 1 ,2213.7  ,407.6,400,392.4
XS GIS Cut Line= 3
     1561632.469      419061.481      1561940.38      418791.517
     1562248.292      418521.553
#Sta/Elev= 30
      10  792.24    79.9  780.67   109.9  774.75   119.9  771.89   129.8  768.45
   169.8   751.2   189.8  743.21   229.7  729.46   249.7  721.92   259.7  717.32
   289.6  701.46   299.6  696.57   309.6  692.08   319.6  688.29   329.6  685.99
   349.6  684.41   389.5  678.47     402  677.22   409.5  677.13     417   678.5
   419.5  678.96   449.5  693.41   569.3  746.23   659.2  786.62   679.2  794.72
   689.2  798.37   709.1  804.77   719.1  808.65   769.1  831.47     819  854.98
#Mann= 3 , 0 , 0
       0     .08       0     402    .045       0     417     .08       0
Bank Sta=402,417
XS Rating Curve= 0 ,0
Exp/Cntr=0.3,0.1

Type RM Length L Ch R = 1 ,1813.7  ,410.1,400,389.8
XS GIS Cut Line= 3
       1562035.7       419411.37     1562237.629      419055.119
     1562439.559      418698.869
#Sta/Elev= 30
      10  816.24      20  812.49      30  807.79    59.9  792.64   149.8  749.01
   179.8  733.55   189.8  729.57   199.8  727.22   219.7  724.02   259.7  712.95
   269.7  708.54   299.6  691.04   309.6  686.17   319.6  683.75   349.6  680.84
     392  674.58   399.5   673.7     407  673.77   409.5   673.8   419.5  676.15
   429.5  681.08   439.5  686.74   469.4  701.75   559.3  745.26   579.3   754.6
   599.3  763.16   619.2  771.01   689.2  797.58   699.1  801.62     819  857.49
#Mann= 3 , 0 , 0
       0     .08       0     392    .045       0     407     .08       0
Bank Sta=392,407
XS Rating Curve= 0 ,0
Exp/Cntr=0.3,0.1

Type RM Length L Ch R = 1 ,1413.7  ,400.4,400,398.8
XS GIS Cut Line= 3
     1562577.506      419579.265     1562594.503       419140.09
     1562607.961      418749.472
#Sta/Elev= 30
      10  785.96      30  779.08    99.9   757.1   119.9  748.98   149.8  734.84
   199.8  717.82   209.8  713.84   239.7  699.85   249.7  696.93   259.7   695.5
   269.7  693.07   289.7  683.94   299.7  680.53   309.7  678.93   349.6  676.26
   409.5  669.95     432   668.3   439.5  668.24     447  669.31   449.5  669.67
   459.5  675.25   489.6     694   549.7  733.46   589.8  755.36   609.9  764.41
   629.9  771.58   710.1  796.62   730.1   803.7   750.2   813.1   830.4  854.55
#Mann= 3 , 0 , 0
       0     .08       0     432    .045       0     447      .1       0
Bank Sta=432,447
XS Rating Curve= 0 ,0
Exp/Cntr=0.3,0.1

Type RM Length L Ch R = 1 ,1013.7  ,413.2,400,387
XS GIS Cut Line= 3
     1562968.543      419651.591     1562977.025      419243.166
     1562967.608      418828.182
#Sta/Elev= 30
      10  792.62    39.9  784.51    69.7   777.6    79.7  774.01   109.6   760.7
   139.5  746.82   179.3  727.13   219.2  708.42   229.2  704.71   249.1  701.23
   259.1  696.43     279  681.91   288.9  675.15   298.9  670.42   308.9  668.52
   318.8  668.25   378.6  668.31   388.6   667.5     401  665.23   408.5   664.5
     416  665.85   418.6  666.33   428.8  670.65   438.9   675.7   580.6  739.23
   651.5  769.61   742.6  806.59     773  818.48   793.2  825.85   823.6  835.85
#Mann= 3 , 0 , 0
       0     .08       0     401    .045       0     416      .1       0
Bank Sta=401,416
XS Rating Curve= 0 ,0
Exp/Cntr=0.3,0.1

Type RM Length L Ch R = 1 ,613.7   ,404,400,398.2
XS GIS Cut Line= 3
     1563557.458      419457.349     1563337.495      419104.846
     1563108.679      418766.516
#Sta/Elev= 30
    10.1  785.56    30.4  778.85    50.7  771.43   111.5  746.27   172.3  722.84
   202.7  710.37     223   702.6   233.1   698.4   243.2  693.19   253.4  686.55
   263.5  682.73   273.6  681.22   283.8  678.77     304  671.67   314.2   669.8
   385.1  663.88     408  660.28   415.5  659.66     423  661.02   425.5  661.47
   435.4   665.8   445.4  671.07   455.4  675.86     555  722.74   584.9  737.94
   704.4  801.01   724.3  811.18   774.1  835.13     804  848.87   823.9  857.55
#Mann= 3 , 0 , 0
       0     .08       0     408    .045       0     423      .1       0
Bank Sta=408,423
XS Rating Curve= 0 ,0
Exp/Cntr=0.3,0.1

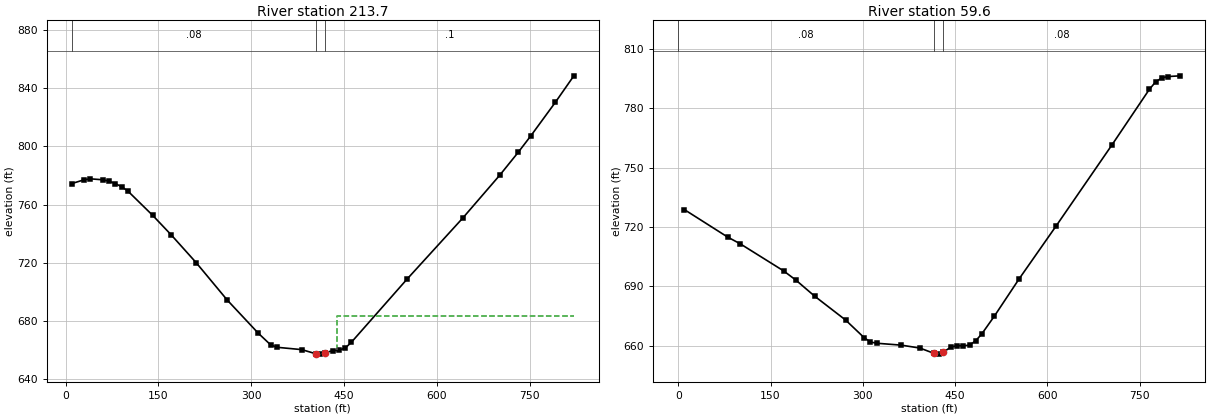
Type RM Length L Ch R = 1 ,213.7   ,154,154.1,152.8
XS GIS Cut Line= 3
     1563966.015      419244.577     1563691.122      418937.819
     1563436.817      418617.004
#Sta/Elev= 30
      10  774.41    30.1  777.03    40.2  777.66    60.3  777.01    70.3  776.03
    80.4  774.37    90.4  772.28   100.5  769.32   140.7  752.55   170.8  739.06
     211  720.01   261.2  694.28   311.4  671.45   331.5  663.39   341.6  661.77
   381.8  660.16   404.4  657.31   411.9  657.07   419.4  658.12   431.9  659.42
   441.9  659.83   451.8  661.22   461.8  665.22   551.7  708.63   641.6  750.59
   701.5  780.13   731.4  795.91   751.4  807.02   791.3  830.24   821.3  848.53
#Mann= 3 , 0 , 0
      10     .08       0   404.4    .045       0   419.4      .1       0
#XS Ineff= 2 , 0
                          438.94          683.14
Permanent Ineff=
       F       F
Bank Sta=404.4,419.4
XS Rating Curve= 0 ,0
Exp/Cntr=0.3,0.1

Type RM Length L Ch R = 1 ,59.6    ,57.2,59.6,62
XS GIS Cut Line= 2
     1564094.241      419159.642     1563551.163      418550.656
#Sta/Elev= 30
    10.1  728.74    80.6  714.81   100.7  711.47   171.3  697.75   191.4  693.05
   221.6     685     272   672.9   302.2  663.97   312.3   661.8   322.4  661.17
   362.7   660.2   392.9  658.72   415.6  656.05   423.1  655.66   430.6  656.67
   443.2  659.19   453.3     660   463.4  659.85   473.5  660.24   483.5  662.42
   493.6  665.99   513.8  674.88     554  693.71   614.5  720.63   705.2  761.61
   765.6  789.54   775.7   793.3   785.7  795.37   795.8  796.06     816  796.42
#Mann= 3 , 0 , 0
       0     .08       0   415.6    .045       0   430.6     .08       0
Bank Sta=415.6,430.6
XS Rating Curve= 0 ,0
Exp/Cntr=0.3,0.1

Chan Stop Cuts=-1
Use User Specified Reach Order=0